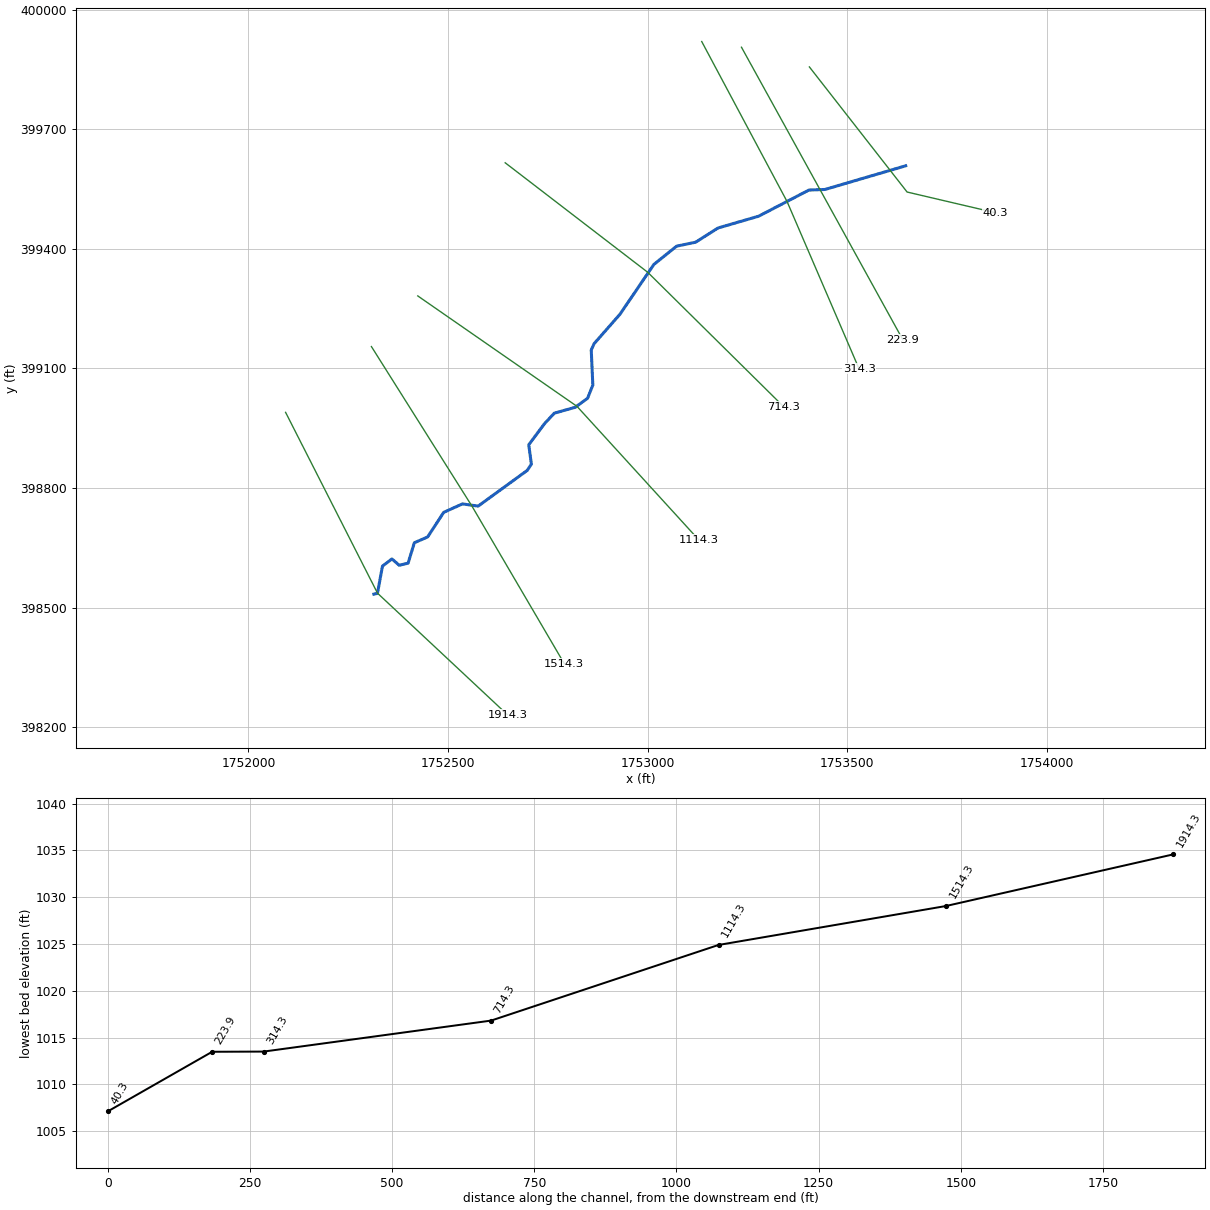
--- GldRn.prj (project) ---

Proj Title=GldRn
Current Plan=p01
Default Exp/Contr=0,0
English Units
Geom File=g01
Flow File=f01
Plan File=p01
BEGIN DESCRIPTION:
END DESCRIPTION:
DSS Export Rating Curves= 0
DSS Export Rating Curve Sorted= 0
DSS Export Volume Flow Curves= 0
DXF OffsetX= 0
DXF OffsetY= 0
DXF ScaleX= 0
DXF ScaleY= 0

--- GldRn.p01 (plan) ---

Plan Title=Floodplain
Program Version=4.00
Geom File=g01
Flow File=f01
K Sum by GR=0
Std Step Tol=0.01
Critical Tol=0.01
Num of Std Step Trials=20
Max Error Tol=0.3
Flow Tol Ratio=0.001
Split Flow NTrial=30
Split Flow Tol=0.02
Split Flow Ratio=0.02
Log Output Level=0
Friction Slope Method=1
Unsteady Friction Slope Method=2
Unsteady Bridges Friction Slope Method=1
Global Log Level=0
CheckData=False
Run HTab=0
Run UNet=0
Run PostProcess=0
UNET Theta=0
UNET Theta Warmup=0
UNET ZTol=0
UNET ZSATol=0
UNET MxIter=0
UNET MaxInSteps=0
UNET DtIC=0
UNET DtMin=0
UNET MaxCRTS=0
UNET WFStab=0
UNET SFStab=0
UNET WFX=0
UNET SFX=0
UNET DSS MLevel=0
UNET DZMax Abort=0
UNET Convert EG Bridges=0
UNET Use Existing IB Tables=0
UNET Froude Limit=0
UNET Froude Power=0
Write IC File=0
Echo Input=False
Echo Output=False
Write Detailed=0

--- GldRn.f01 (steady flow) ---

Flow Title=NFF Regression Equation
Program Version=4.00
Number of Profiles=1
Profile Names=P100yr
River Rch & RM=GldRn,Main      ,1914.3
517.0432
River Rch & RM=GldRn,Main      ,314.3
574.1792
Boundary for River Rch & Prof#=GldRn,Main      ,1
Up Type=0
Dn Type=3
Dn Slope=0.00541

--- GldRn.g01 (geometry) ---

Geom Title=USGS 3m DEM
Program Version=4.00

River Reach=GldRn           ,Main
Reach XY= 30
     1752314.329      398533.696     1752323.179      398535.453
     1752335.763      398603.918     1752359.445      398621.974
     1752377.828      398606.063     1752399.936      398611.309
     1752415.633      398662.528     1752448.969      398677.082
     1752489.227      398738.839     1752536.178      398759.993
     1752575.532      398754.468      1752698.18      398843.794
     1752708.898      398859.701     1752702.226      398908.303
     1752741.842      398961.334     1752766.254      398987.566
     1752818.725      399002.323     1752849.578      399024.898
     1752862.804      399058.064      1752858.83       399146.09
     1752866.052      399161.965     1752930.836      399235.788
     1753015.658       399360.61     1753072.597      399406.472
     1753120.397      399416.507     1753176.492      399452.118
     1753278.124      399481.663     1753404.203      399547.271
     1753444.418      399548.762     1753646.738      399608.167

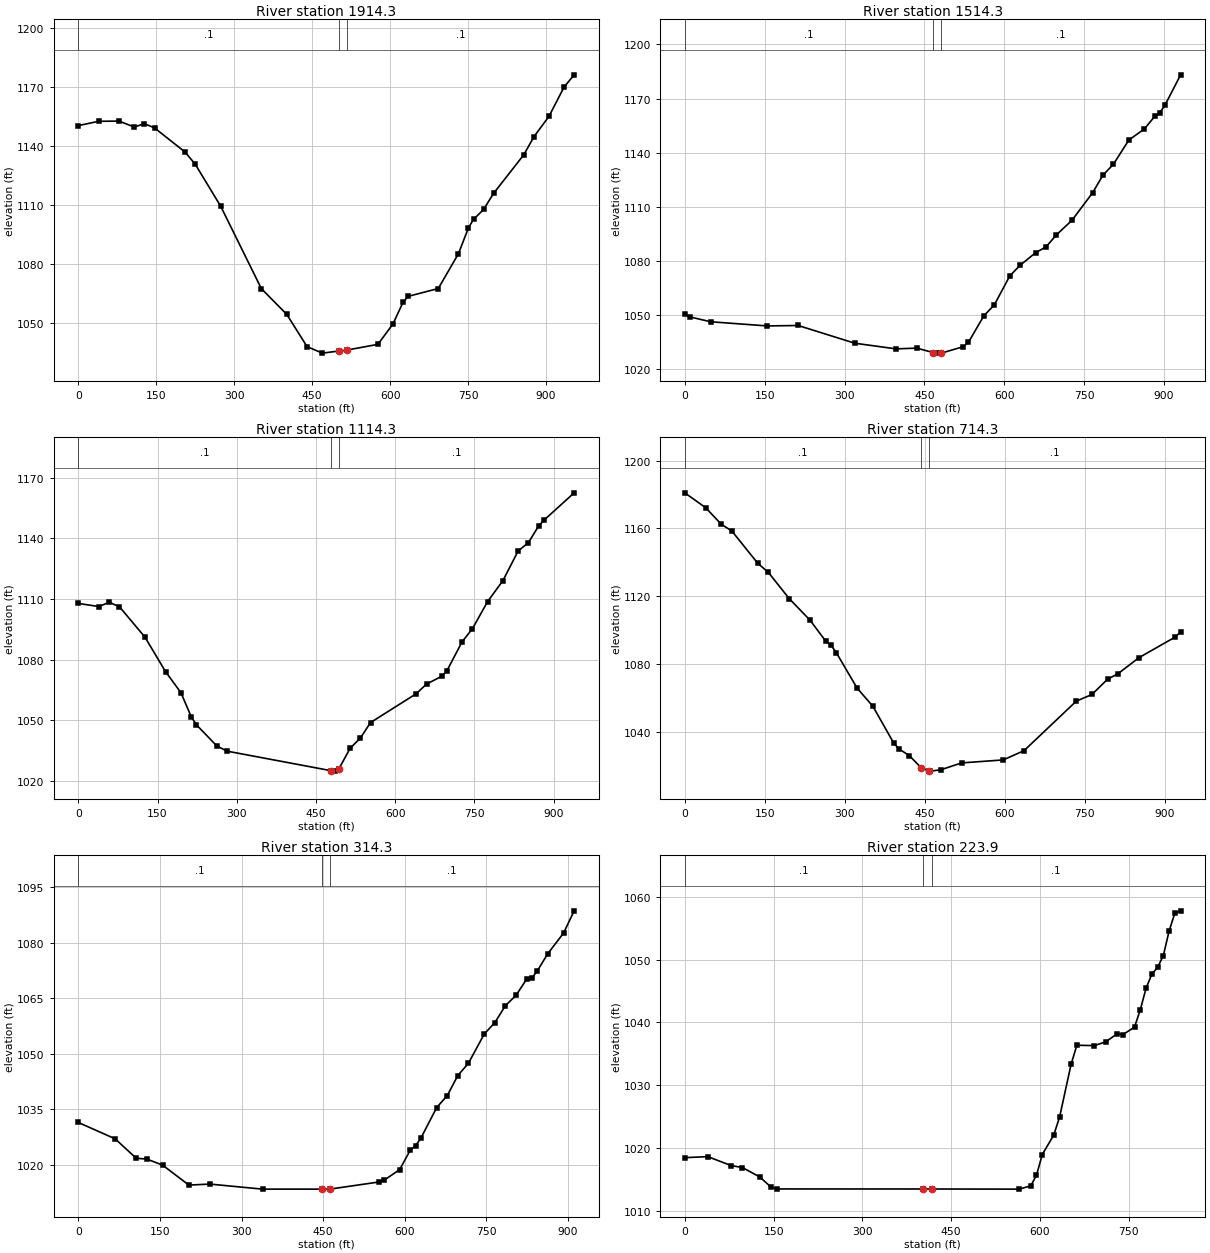
Type RM Length L Ch R = 1 ,1914.3  ,368.626,400,389.214
XS GIS Cut Line= 3
     1752093.065      398989.676     1752323.308      398536.067
     1752648.466      398231.523
#Sta/Elev= 30
       0 1150.37    39.1 1152.57    78.3 1152.67   107.6 1149.66   127.2 1151.35
   146.7 1149.19   205.4 1136.91     225  1130.7   273.9 1109.36   352.2 1067.41
   401.1 1054.29   440.2 1037.88   469.6 1034.57   501.2 1035.63   516.2 1036.09
   576.5 1039.04   605.5 1049.41   624.9 1060.47   634.6 1063.46   692.7 1067.45
   731.5 1085.18   750.8 1098.36   760.5 1102.61   779.9 1107.71   799.2  1115.9
   857.4 1135.58   876.7 1144.67   905.8 1155.11   934.8    1170   954.2 1176.22
#Mann= 3 , 0 , 0
       0      .1       0   501.2    .045       0   516.2      .1       0
Bank Sta=501.2,516.2
XS Rating Curve= 0 ,0
Exp/Cntr=0.3,0.1

Type RM Length L Ch R = 1 ,1514.3  ,392.753,400,404.138
XS GIS Cut Line= 3
     1752308.063      399154.735     1752560.613      398753.336
     1752791.392      398359.012
#Sta/Elev= 30
       0 1050.84     9.7  1049.1    48.4 1046.42   154.9 1044.11   212.9 1044.35
   319.4 1034.52   396.8 1031.41   435.5 1031.82   466.7 1029.35   474.2 1029.05
   481.7 1029.06   522.8  1032.6   532.6 1035.01   561.7 1049.76   581.2 1055.74
   610.3  1071.8   629.8 1077.73   658.9 1084.68   678.4 1087.89   697.8 1094.52
     727 1102.59   765.9 1117.88   785.3 1127.63   804.8  1133.6   833.9 1147.07
   863.1 1153.21   882.5 1160.19   892.2 1162.24     902 1166.53   931.1 1183.16
#Mann= 3 , 0 , 0
       0      .1       0   466.7    .045       0   481.7      .1       0
Bank Sta=466.7,481.7
XS Rating Curve= 0 ,0
Exp/Cntr=0.3,0.1

Type RM Length L Ch R = 1 ,1114.3  ,404.163,400,400.966
XS GIS Cut Line= 3
     1752424.216      399281.742     1752823.131      399004.689
     1753128.271      398669.814
#Sta/Elev= 30
       0 1107.87    38.9 1106.32    58.3 1108.41    77.7 1106.27   126.3 1091.12
   165.1 1074.12   194.3 1063.68   213.7  1051.8   223.4 1047.85   262.3 1037.31
   281.7 1034.77   478.2 1025.12   485.7 1024.89   493.2 1025.95   514.6 1036.22
   533.9 1041.22   553.2 1048.92   639.9 1063.22   659.2 1067.97   688.1 1071.83
   697.8 1074.57   726.7 1088.94   745.9 1095.27   774.9 1108.81   803.8 1119.15
   832.7 1133.85     852 1137.91   871.3 1146.13   880.9  1148.9   938.7 1162.59
#Mann= 3 , 0 , 0
       0      .1       0   478.2    .045       0   493.2      .1       0
Bank Sta=478.2,493.2
XS Rating Curve= 0 ,0
Exp/Cntr=0.3,0.1

Type RM Length L Ch R = 1 ,714.3   ,409.676,400,391.257
XS GIS Cut Line= 3
      1752643.29      399615.692     1753000.479       399340.88
     1753341.281      399003.545
#Sta/Elev= 30
       0 1180.96    39.2 1172.17    68.6 1162.37    88.2 1158.47   137.2 1139.29
   156.8 1134.03   195.9 1118.55   235.1 1105.79   264.5  1093.4   274.3 1091.04
   284.1 1086.77   323.3 1065.74   352.7 1055.13   391.9 1033.39   401.7 1029.91
   421.3 1025.93   443.2  1018.9   458.2 1016.92   460.5 1016.81     480 1017.57
   519.2 1021.65   597.5 1023.43   636.6 1028.92   734.5  1058.1   763.8 1062.01
   793.2 1071.03   812.8 1074.29   851.9 1083.71   920.4 1095.96   930.2 1099.05
#Mann= 3 , 0 , 0
       0      .1       0   443.2    .045       0   458.2      .1       0
Bank Sta=443.2,458.2
XS Rating Curve= 0 ,0
Exp/Cntr=0.3,0.1

Type RM Length L Ch R = 1 ,314.3   ,89.277,90.428,92.761
XS GIS Cut Line= 3
     1753135.655      399919.845      1753349.42      399518.551
     1753529.839      399098.862
#Sta/Elev= 30
       0 1031.48    67.7 1027.07   106.4 1021.82   125.8 1021.61   154.8 1019.99
   203.2 1014.59   241.8 1014.86   338.6  1013.5   447.2  1013.5   462.2  1013.5
   551.9 1015.41   561.6 1015.84   590.8 1018.78   610.2 1024.02   619.9  1025.2
   629.6 1027.22   658.8 1035.51   678.2 1038.73   697.7 1044.15   717.1 1047.45
   746.3 1055.37   765.7 1058.41   785.1 1062.99   804.6 1065.77     824  1070.1
   833.7 1070.44   843.5  1072.3   862.9 1076.99   892.1 1082.59   911.5 1088.57
#Mann= 3 , 0 , 0
       0      .1       0   447.2    .045       0   462.2      .1       0
Bank Sta=447.2,462.2
XS Rating Curve= 0 ,0
Exp/Cntr=0.3,0.1

Type RM Length L Ch R = 1 ,223.9   ,180.549,183.607,187.264
XS GIS Cut Line= 2
     1753235.223      399905.593     1753639.404      399171.977
#Sta/Elev= 30
       0 1018.49      39 1018.65    77.9 1017.24    97.4 1016.91   126.6 1015.42
   146.1 1013.77   155.8 1013.51   401.9  1013.5   416.9  1013.5   564.9 1013.48
   584.4    1014   594.1 1015.69   603.8 1018.97   623.3  1022.1   633.1 1024.93
   652.5 1033.33   662.3 1036.38   691.5 1036.32     711 1036.91   730.5 1038.21
   740.2 1038.08   759.7 1039.26   769.4    1042   779.2 1045.44   788.9 1047.68
   798.6 1048.76   808.4 1050.65   818.1 1054.55   827.8 1057.39   837.6 1057.77
#Mann= 3 , 0 , 0
       0      .1       0   401.9    .045       0   416.9      .1       0
Bank Sta=401.9,416.9
XS Rating Curve= 0 ,0
Exp/Cntr=0.3,0.1

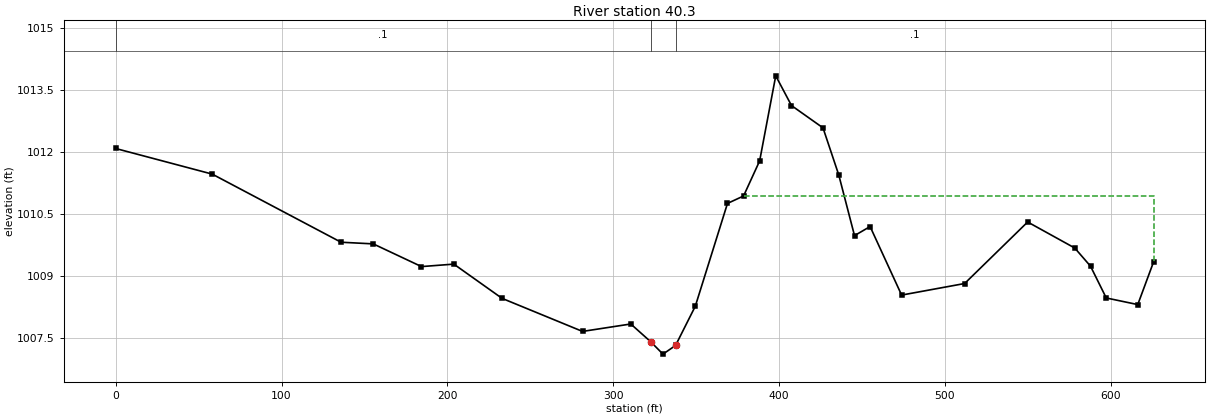
Type RM Length L Ch R = 1 ,40.3    ,48.58,40.26,32.041
XS GIS Cut Line= 3
     1753405.379      399856.146     1753650.177      399542.336
     1753871.947      399490.339
#Sta/Elev= 30
       0 1012.09    58.2 1011.47   135.9 1009.82   155.3 1009.78   184.4 1009.23
   203.9 1009.29     233 1008.46   281.5 1007.66   310.6 1007.84   322.6 1007.41
     330 1007.11   337.6 1007.32   349.5 1008.27   368.9 1010.76   378.6 1010.94
   388.3 1011.79     398 1013.85   407.5 1013.13   426.5 1012.59     436 1011.45
   445.5 1009.98   454.9  1010.2   473.9 1008.54   511.9 1008.82   549.9 1010.31
   578.3 1009.68   587.8 1009.24   597.3 1008.47   616.3 1008.31   625.8 1009.34
#Mann= 3 , 0 , 0
       0      .1       0   322.6    .045       0   337.6      .1       0
#XS Ineff= 2 , 0
                          378.83         1010.94
Permanent Ineff=
       F       F
Bank Sta=322.6,337.6
XS Rating Curve= 0 ,0
Exp/Cntr=0.3,0.1

Chan Stop Cuts=-1
Use User Specified Reach Order=0